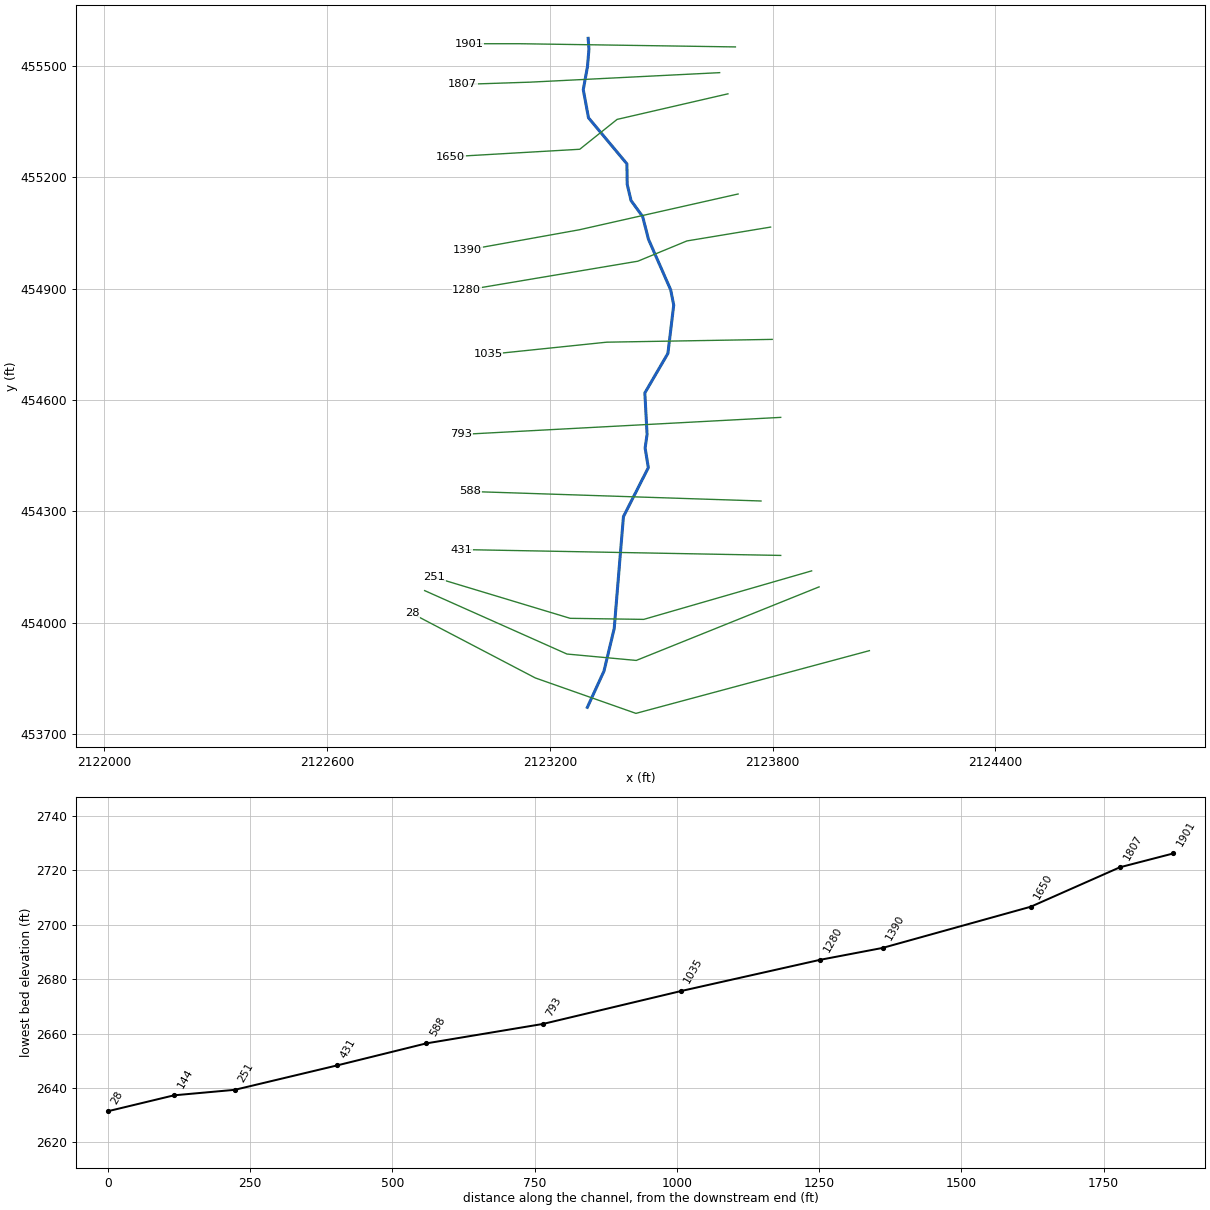
--- HUNTERSRN.prj (project) ---

Proj Title=HUNTERSRN
Current Plan=p01
Default Exp/Contr=0,0
English Units
Geom File=g01
Flow File=f01
Plan File=p01
BEGIN DESCRIPTION:
Stream Name- Hunters Run
Flood Zone: Zone A
Greenbrier County, WV
County-Wide Study
WVDHSEM-2018-3, Flood Risk Project
HEC-RAS Version: 5.0.7
General Notes:
For the Hydrology Regression was used.
END DESCRIPTION:
DSS Export Rating Curves= 0
DSS Export Rating Curve Sorted= 0
DSS Export Volume Flow Curves= 0
DXF Filename=..\..\..\..\..\fz_Working\Nov1\Models\HUNTERSRN\HUNTERSRN.
DXF OffsetX= 0
DXF OffsetY= 0
DXF ScaleX= 0
DXF ScaleY= 0

--- HUNTERSRN.p01 (plan) ---

Plan Title=Floodplain
Program Version=5.07
Short Identifier=Floodplain
Geom File=g01
Flow File=f01
Subcritical Flow
K Sum by GR= 0
Std Step Tol= 0.01
Critical Tol= 0.01
Num of Std Step Trials= 20
Max Error Tol= 0.3
Flow Tol Ratio= 0.001
Split Flow NTrial= 30
Split Flow Tol= 0.02
Split Flow Ratio= 0.02
Log Output Level= 0
Friction Slope Method= 1
Unsteady Friction Slope Method= 2
Unsteady Bridges Friction Slope Method= 1
Parabolic Critical Depth
Global Vel Dist= 0 , 0 , 0
Global Log Level= 0
CheckData=False
Encroach Param=-1 ,0,0, 0
Mapping Interval=1HOUR
Computation Time Step Use Courant=        0
Computation Time Step Use Time Series=    0
Computation Time Step Count To Double=0
Computation Time Step Max Doubling=0
Computation Time Step Max Halving=0
Computation Time Step Residence Courant=0
Run HTab= 0
Run UNet= 0
Run Sediment= 0
Run PostProcess= 0
Run WQNet= 0
Run RASMapper= 0
UNET Theta= 0
UNET Theta Warmup= 0
UNET ZTol= 0
UNET ZSATol= 0
UNET MxIter= 0
UNET Max Iter WO Improvement= 0
UNET MaxInSteps= 0
UNET DtIC= 0
UNET DtMin= 0
UNET MaxCRTS= 0
UNET WFStab= 0
UNET SFStab= 0
UNET WFX= 1
UNET SFX= 1
UNET 1D Methodology=Finite Difference
UNET DSS MLevel= 1
UNET Pardiso=0
UNET DZMax Abort= 0
UNET Use Existing IB Tables= 0
UNET Froude Reduction=False
UNET Froude Limit= 0
UNET Froude Power= 0
UNET D1 Cores= 0
UNET D2 Coriolis=0
UNET D2 Cores= 0
UNET D2 Theta= 1
UNET D2 Theta Warmup= 1
UNET D2 Z Tol= 0.01
UNET D2 Volume Tol= 0.01
UNET D2 Max Iterations= 20
UNET D2 Equation= 0
UNET D2 RampUpFraction=0.1
UNET D2 TimeSlices= 1
UNET D2 BCVolumeCheck=0
UNET D1D2 MaxIter= 0
UNET D1D2 ZTol=0.01
UNET D1D2 QTol=0.1
UNET D1D2 MinQTol=1
Write IC File= 0
Write IC File at Fixed DateTime=0
Write IC File at Sim End=0
Echo Input=False
Echo Parameters=False
Echo Output=False
Write Detailed= 0
HDF Write Warmup=0
HDF Write Time Slices=0
HDF Flush=0
HDF Face Node Velocities=0
HDF Compression= 1
HDF Chunk Size= 1
HDF Spatial Parts= 1
HDF Use Max Rows=0
HDF Fixed Rows= 1
Calibration Method= 0
Calibration Iterations= 20
Calibration Max Change=0.05
Calibration Tolerance=0.2
Calibration Maximum=1.5
Calibration Minimum=0.5
Calibration Optimization Method= 1
WQ AD Non Conservative
WQ ULTIMATE=-1
WQ Max Comp Step=1HOUR
WQ Output Interval=15MIN
WQ Output Selected Increments= 0
WQ Output face flow=0
WQ Output face velocity=0
WQ Output face area=0
WQ Output face dispersion=0
WQ Output cell volume=0
WQ Output cell surface area=0
WQ Output cell continuity=0
WQ Output cumulative cell continuity=0
WQ Output face conc=0
WQ Output face dconc_dx=0
WQ Output face courant=0
WQ Output face peclet=0
WQ Output face adv mass=0
WQ Output face disp mass=0
WQ Output cell mass=0
WQ Output cell source sink temp=0
WQ Output nsm pathways=0
WQ Output nsm derived pathways=0
WQ Output MaxMinRange=-1
WQ Daily Max Min Mean=-1
WQ Daily Range=0
WQ Daily Time=0
WQ Create Restart=0
WQ Fixed Restart=0
WQ System Summary=0
WQ Write To DSS=0
WQ Use Fixed Temperature=0
Sorting and Armoring Iterations= 10
XS Update Threshold= 0.02
Bed Roughness Predictor= 0
Hydraulics Update Threshold= 0.02
Energy Slope Method= 1
Volume Change Method= 1
Sediment Retention Method= 0
XS Weighting Method= 0
Number of US Weighted Cross Sections= 1
Number of DS Weighted Cross Sections= 1
Upstream XS Weight=0
Main XS Weight=1
Downstream XS Weight=0
Number of DS XS's Weighted with US Boundary= 1
Upstream Boundary Weight= 1
Weight of XSs Associated with US Boundary= 0
Number of US XS's Weighted with DS Boundary= 1
Downstream Boundary Weight= 0.5
Weight of XSs Associated with DS Boundary= 0.5
Percentile Method= 0
Sediment Output Level= 3
Mass or Volume Output= 0
Output Increment Type= 1
Profile and TS Output Increment= 1
XS Output Flag= 0
XS Output Increment= 10
Write Gradation File= 0
Read Gradation Hotstart= 0
Write HDF5 File= 1
Write Binary Output= 1
Write DSS Sediment File= 0
SV Curve= 0
Specific Gage Flag= 0

--- HUNTERSRN.f01 (steady flow) ---

Flow Title=NFF Regression Equation
Program Version=5.07
Number of Profiles= 6
Profile Names=f1p,f10p,f4p,f2p,f02p,f1pplus
River Rch & RM=HUNTERSRN,Main            ,1901
     781     418     552     663    1080    1160
Boundary for River Rch & Prof#=HUNTERSRN,Main            , 1
Up Type= 0
Dn Type= 3
Dn Slope=0.0502
Boundary for River Rch & Prof#=HUNTERSRN,Main            , 2
Up Type= 0
Dn Type= 3
Dn Slope=0.0502
Boundary for River Rch & Prof#=HUNTERSRN,Main            , 3
Up Type= 0
Dn Type= 3
Dn Slope=0.0502
Boundary for River Rch & Prof#=HUNTERSRN,Main            , 4
Up Type= 0
Dn Type= 3
Dn Slope=0.0502
Boundary for River Rch & Prof#=HUNTERSRN,Main            , 5
Up Type= 0
Dn Type= 3
Dn Slope=0.0502
Boundary for River Rch & Prof#=HUNTERSRN,Main            , 6
Up Type= 0
Dn Type= 3
Dn Slope=0.0502
DSS Import GetInterval= 0
DSS Import GetPeak= 0
DSS Import FillOption= 0

--- HUNTERSRN.g01 (geometry) ---

Geom Title=USGS 10m DEM
Program Version=5.07

River Reach=HUNTERSRN       ,Main
Reach XY= 21
2123303.15991524 455574.645980792123305.32387926455545.724043801
2123301.33037381455498.231740907 2123289.9869172455436.654360592
2123304.06184819455360.5570423162123407.57614549455236.546731576
2123408.34264283455181.297301576 2123418.7181913455137.661419421
2123450.07531072455094.2812752722123465.60988471455033.381052345
2123525.47088721454897.1755313132123533.68642801454856.044556677
2123518.02072017454725.8654719142123455.90177044454619.345322892
2123461.87424445454507.7485760752123456.63697729454470.922941968
2123465.27679506454418.0432572812123398.23959947454286.119458094
2123373.28970376453984.3938165012123345.72560948453869.778157204
2123300.97795996453772.350658685

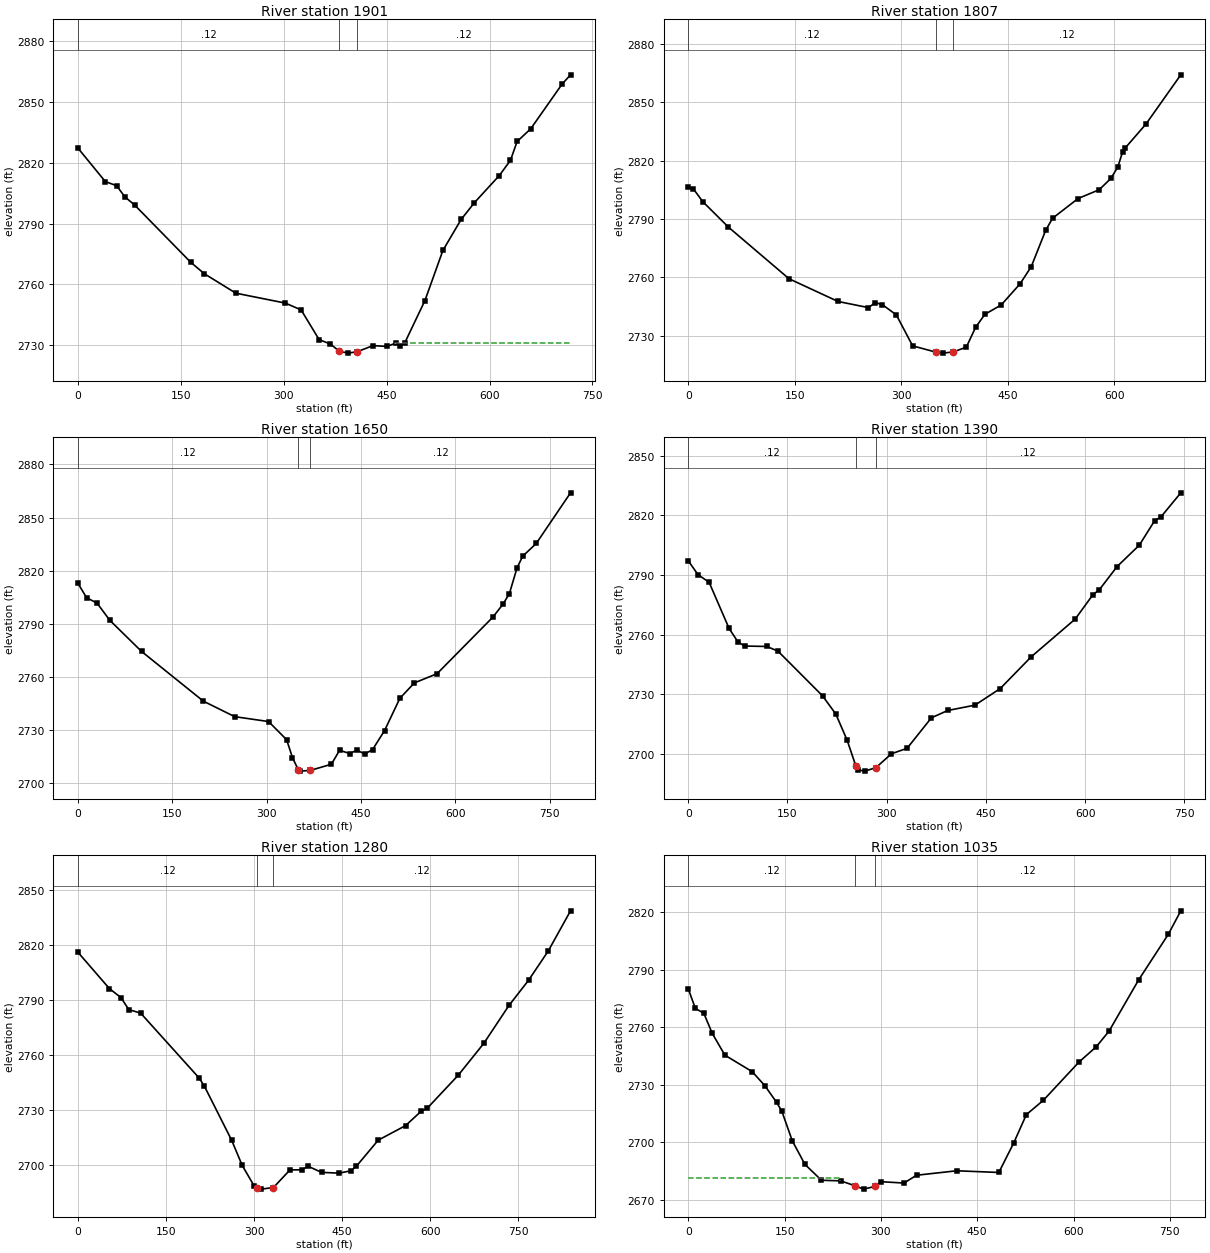
Type RM Length L Ch R = 1 ,1901    ,93.2,94.1,94.6
XS GIS Cut Line= 3
2123699.86801188455551.5151802122123119.72231869455560.131205358
2122981.86591635455560.131205358
#Sta/Elev= 30
       0 2827.14    39.8 2810.69    56.2 2808.67    68.3 2803.14    82.5 2799.14
   164.5 2770.83   184.2 2765.24   230.1 2755.66   302.3 2750.77   325.3 2747.39
   351.5 2732.77   367.9 2730.59   381.1 2727.01   394.2  2726.1   407.3 2726.84
   430.3 2729.82     450 2729.39   463.1 2730.99   469.7 2729.67   476.2 2731.03
   505.8 2752.02     532 2776.76   558.6 2792.01   577.9 2800.28   614.1 2813.61
   630.5 2821.15   640.2 2830.46     660  2836.7   705.9 2858.82   718.1 2863.33
#Mann= 3 , 0 , 0
       0     .12       0   381.1     .04       0   407.3     .12       0
#XS Ineff= 2 , 0
                          461.74         2731.23
Permanent Ineff=
       F       F
Bank Sta=381.1,407.3
XS Rating Curve= 0 ,0
Exp/Cntr(USF)=0,0
Exp/Cntr=0.3,0.1

Type RM Length L Ch R = 1 ,1807    ,148,156.7,160.8
XS GIS Cut Line= 3
2123657.42082481 455482.200285462123146.71983954455456.589911567
2122964.43423713 455450.56394124
#Sta/Elev= 30
       0 2806.42     7.2  2805.4    20.4 2798.86    56.5 2785.78   141.9 2759.23
   210.9 2747.56   253.6 2744.41   263.5 2746.93   273.3 2745.94     293 2740.67
     316 2724.75   348.72721.523   358.7 2721.01   373.22721.627   391.6 2724.08
   404.7 2734.27   417.8 2740.97   440.8 2745.77   467.5 2756.72   483.1 2765.48
   503.3 2784.04   513.1 2790.32     549 2800.46   578.8 2804.99   595.2 2810.78
     605 2816.66   611.6 2824.28   614.9 2826.23   644.7 2838.76   693.7 2864.04
#Mann= 3 , 0 , 0
       0     .12       0   348.7     .04       0   373.2     .12       0
Bank Sta=348.7,373.2
XS Rating Curve= 0 ,0
Exp/Cntr(USF)=0,0
Exp/Cntr=0.3,0.1

Type RM Length L Ch R = 1 ,1650    ,265,260.4,255.6
XS GIS Cut Line= 4
 2123679.7639532455425.1468113992123381.07508146455356.218610229
2123280.55478809 455275.802375532122933.04177386455255.698316855
#Sta/Elev= 30
       0 2812.71    13.5 2804.67    30.3 2801.55    50.5 2791.87     101 2774.26
   199.3 2746.12   249.2 2737.35   303.1 2734.57   331.8  2724.3   341.1 2714.15
   350.4 2707.24     353 2706.53   369.4 2706.93     403 2710.43     416 2718.31
   432.1  2716.5   443.5 2718.32   456.2 2716.27   468.4 2718.66   487.6  2729.5
   511.9 2747.72   534.9 2756.43   571.1 2761.65   659.8 2793.63     676 2800.98
   686.1 2806.93   698.3 2821.51   707.3 2828.13   728.8 2835.31   783.4 2863.97
#Mann= 3 , 0 , 0
       0     .12       0   350.4     .04       0   369.4     .12       0
Bank Sta=350.4,369.4
XS Rating Curve= 0 ,0
Exp/Cntr(USF)=0,0
Exp/Cntr=0.3,0.1

Type RM Length L Ch R = 1 ,1390    ,106.9,109.9,111.8
XS GIS Cut Line= 3
2123707.13508001455155.2913951852123279.29118675455058.875869942
2122977.99267037455004.642136993
#Sta/Elev= 30
       0 2797.11    14.6  2790.2    31.5 2786.31    61.7 2763.11    75.2 2756.29
    85.3 2754.29   118.9 2754.06   135.7 2751.69     203 2729.25   223.1 2720.08
     240 2707.11   253.4 2693.97   256.8 2692.03   266.9 2691.41   283.7 2693.15
   307.2 2700.15   330.8 2702.86   367.6 2718.21   392.3 2721.89   433.5 2724.57
   471.7 2732.92   518.4 2748.83   585.1 2767.86   611.7 2780.02   621.7 2782.66
   648.4 2794.23     682 2804.99   705.1 2817.25   715.1 2819.35   744.7 2831.29
#Mann= 3 , 0 , 0
       0     .12       0   253.4     .04       0   283.7     .12       0
Bank Sta=253.4,283.7
XS Rating Curve= 0 ,0
Exp/Cntr(USF)=0,0
Exp/Cntr=0.3,0.1

Type RM Length L Ch R = 1 ,1280    ,250.5,244.8,240.1
XS GIS Cut Line= 4
2123794.64428849455066.1457636372123569.19163049 455028.80965467
2123437.07924491 454974.241495412122976.12189959454896.697269093
#Sta/Elev= 30
       0 2816.11    53.3  2796.4    73.2 2791.42    86.5 2784.87   106.5 2783.03
   206.3  2747.6   215.3 2743.11   261.6 2713.72   279.6 2699.99   299.7 2688.92
   304.8 2687.78   312.3 2687.04   332.9 2687.92     361 2697.53   381.6 2697.55
   391.6 2699.55   414.8 2696.17   444.8 2695.76   464.7 2697.04     474 2699.47
   511.3 2713.73   557.9 2721.67   584.5  2729.5   594.5 2731.03   647.7 2749.16
     691 2766.44   734.2 2787.24   767.5 2800.93   800.8  2816.8   838.9 2838.75
#Mann= 3 , 0 , 0
       0     .12       0   304.8     .04       0   332.9     .12       0
Bank Sta=304.8,332.9
XS Rating Curve= 0 ,0
Exp/Cntr(USF)=0,0
Exp/Cntr=0.3,0.1

Type RM Length L Ch R = 1 ,1035    ,242.2,241.9,242.4
XS GIS Cut Line= 3
2123799.03112751454763.6033238872123353.10932326454756.070860978
 2123033.7328959454722.928024175
#Sta/Elev= 30
       0 2780.11      11 2769.89    24.2 2767.37    37.3 2756.89      57  2745.5
    99.6 2736.87   119.3 2729.54   137.4 2720.93   145.6 2716.33     162 2700.76
   181.7 2688.48   207.4 2680.19   237.5 2679.87   260.4 2677.22   272.9 2675.56
   291.42677.001   299.8 2679.45   335.9 2678.73   355.6 2682.81   418.1 2685.14
   483.7 2684.26   506.8 2699.61   526.6 2714.48     553 2721.92   608.4 2741.86
   635.5 2749.91   655.3 2758.02   701.4 2784.77   747.6 2808.57   767.1 2820.86
#Mann= 3 , 0 , 0
       0     .12       0   260.4     .04       0   291.4     .12       0
#XS Ineff= 2 , 0
          236.52 2681.27
Permanent Ineff=
       F       F
Bank Sta=260.4,291.4
XS Rating Curve= 0 ,0
Exp/Cntr(USF)=0,0
Exp/Cntr=0.3,0.1

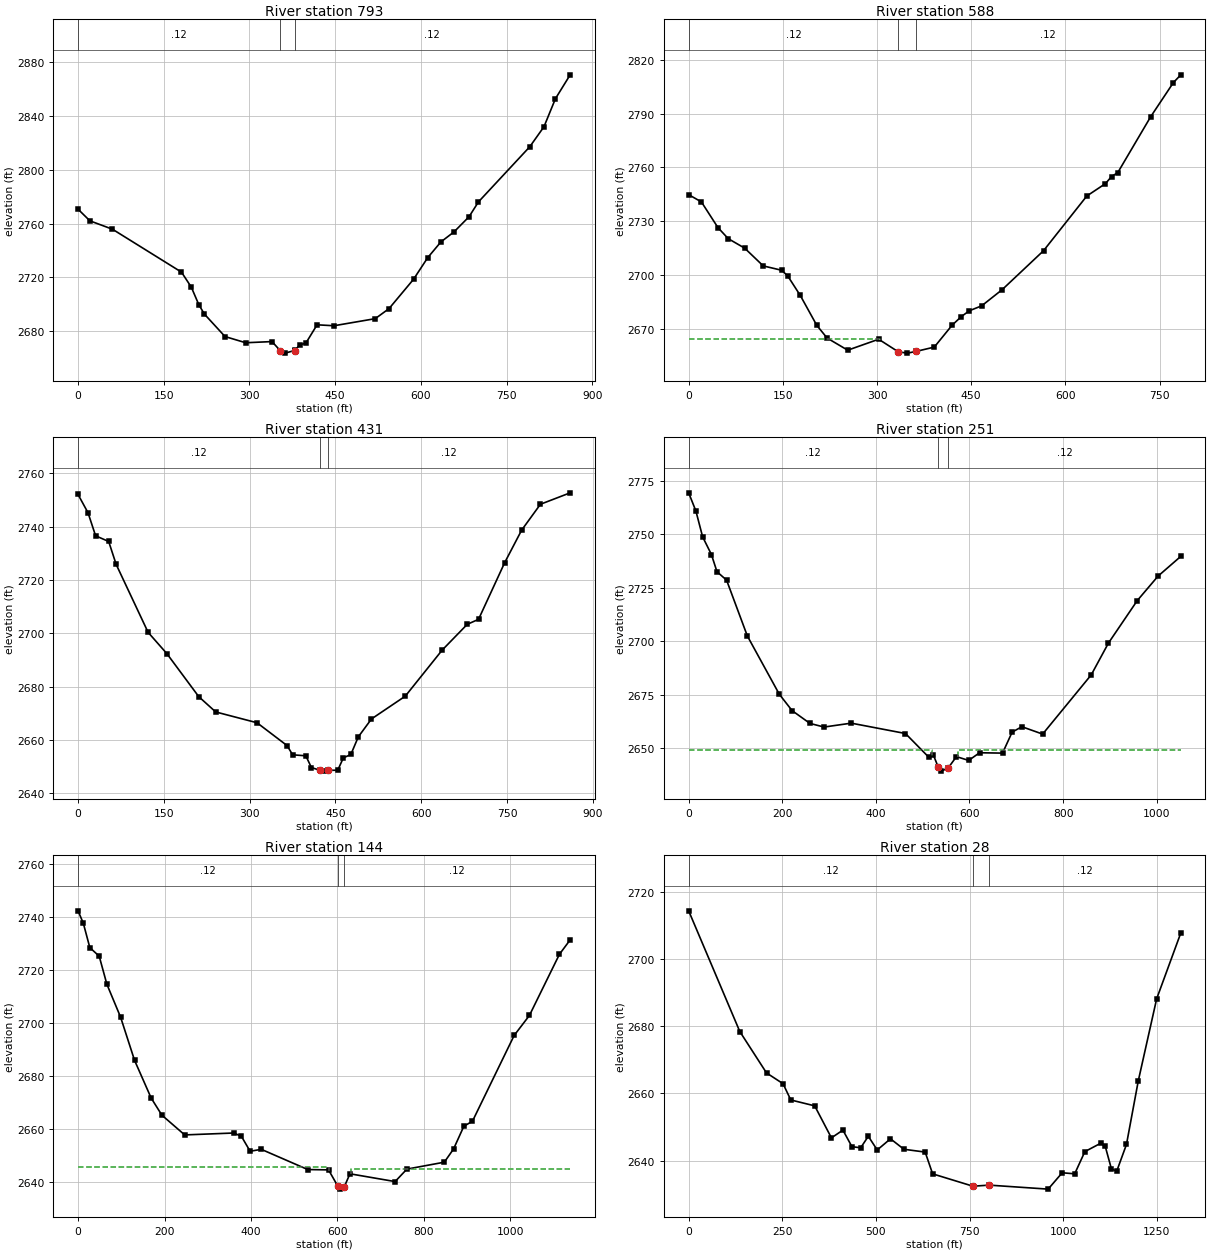
Type RM Length L Ch R = 1 ,793     ,205,205.4,201.9
XS GIS Cut Line= 2
2123821.92836812454553.4922674322122961.76185768454507.540133319
#Sta/Elev= 30
       0 2770.72    20.8 2762.03    60.3 2755.79   181.1 2723.83   198.3 2712.64
   211.4 2699.61   221.2 2692.59   257.3 2675.86   293.5 2671.25   339.5 2672.12
     354 2665.35   362.5 2663.52     379 2665.47     379 2665.48   388.8 2669.81
   398.7  2670.9   418.4 2684.61     448 2683.91   520.2 2689.19   544.3 2696.64
   587.2 2718.48   612.2 2734.69   635.2 2746.36   658.2 2753.84   684.4  2765.1
   700.9 2776.16   790.7 2817.21   815.6 2832.15   835.6 2852.99   861.4 2870.77
#Mann= 3 , 0 , 0
       0     .12       0     354     .04       0     379     .12       0
Bank Sta=354,379
XS Rating Curve= 0 ,0
Exp/Cntr(USF)=0,0
Exp/Cntr=0.3,0.1

Type RM Length L Ch R = 1 ,588     ,156.6,156.8,155.2
XS GIS Cut Line= 2
2123768.90127587454328.2269677142122985.52513328454353.837341607
#Sta/Elev= 30
       0 2744.78    20.3 2740.72    46.6 2726.42      63 2720.23    89.2 2714.93
   118.8 2705.02   148.3 2702.58   157.9 2699.35   177.8 2688.52   204.1 2671.84
   220.5 2664.78   253.3 2658.01   302.6 2664.12   334.12657.054   348.5 2656.37
   361.7 2657.29   391.2 2659.74   419.7 2672.01   434.4  2676.8     447    2680
   466.7 2682.76   499.5 2691.84   565.2 2713.51   634.1 2744.02   663.7 2750.91
   673.5 2754.88   683.4 2757.07   735.9 2788.29     772  2807.3   783.8 2811.62
#Mann= 3 , 0 , 0
       0     .12       0   334.1     .04       0   361.7     .12       0
#XS Ineff= 2 , 0
          305.22 2664.04
Permanent Ineff=
       F       F
Bank Sta=334.1,361.7
XS Rating Curve= 0 ,0
Exp/Cntr(USF)=0,0
Exp/Cntr=0.3,0.1

Type RM Length L Ch R = 1 ,431     ,179.4,179.7,179.8
XS GIS Cut Line= 2
2123821.92836812 454181.567181952122961.76185768454197.363228052
#Sta/Elev= 30
       0 2752.08    17.5  2745.2    30.7 2736.58    53.6 2734.43    66.7 2725.82
   122.5 2700.35   155.3 2692.36   211.1 2676.21   240.7 2670.48   312.9 2666.43
   365.4 2657.87   375.2  2654.4   398.2 2654.03     408 2649.62   422.4 2648.64
     431 2648.28   437.42648.575     454 2648.62   463.8 2653.26   476.9 2654.52
     490 2661.15     513 2667.86   572.1 2676.41   636.5 2693.67   680.4 2703.36
   700.1 2705.22   745.9 2726.53   775.5  2738.7   808.3  2748.4   860.3 2752.69
#Mann= 3 , 0 , 0
       0     .12       0   422.4     .04       0   437.4     .12       0
Bank Sta=422.4,437.4
XS Rating Curve= 0 ,0
Exp/Cntr(USF)=0,0
Exp/Cntr=0.5,0.3

Type RM Length L Ch R = 1 ,251     ,109,106.8,106.4
XS GIS Cut Line= 4
 2123905.2166112 454139.923060412123452.87529102454009.246679024
2123254.70671265454012.1186874062122888.52564393454122.691010117
#Sta/Elev= 30
       0 2769.27    15.5 2760.74    29.8 2748.74    48.6 2740.47    60.5 2732.43
      81 2728.51   125.4 2702.42   193.7 2675.21     221 2667.58   259.2  2661.6
   289.3 2659.91   347.4 2661.73   463.2 2656.89     513 2645.83   522.9 2646.85
   532.7 2641.46   539.3 2639.33   554.12640.689   572.1  2646.1   598.3 2644.33
   621.5 2647.91   670.6 2647.74   691.1 2657.53   711.9 2660.07   756.3 2656.62
   860.2  2684.3   896.8 2699.09   958.5 2718.97    1003 2730.41  1051.5 2739.61
#Mann= 3 , 0 , 0
       0     .12       0   532.7     .04       0   554.1     .12       0
#XS Ineff= 2 , 0
          519.13 2649.32  575.22         2649.32
Permanent Ineff=
       F       F
Bank Sta=532.7,554.1
XS Rating Curve= 0 ,0
Exp/Cntr(USF)=0,0
Exp/Cntr=0.5,0.3

Type RM Length L Ch R = 1 ,144     ,119.4,116.2,115.7
XS GIS Cut Line= 4
2123925.32066987454096.8429346782123432.77123234453898.674356313
2123246.09068751453915.906406606 2122862.6775685454086.790905341
#Sta/Elev= 30
       0 2742.39    12.2 2737.73    27.3  2728.5      49 2725.26    66.7 2714.68
    98.5 2702.22   130.7 2685.95   169.2 2671.68     194 2665.23   246.7 2657.78
   360.2  2658.5   377.9 2657.24     398 2651.61   423.9 2652.33   531.4  2644.7
   579.4 2644.58   600.62638.487   605.8 2637.31   615.82638.201   628.9  2643.1
   733.3 2640.16   760.6 2644.87   847.1 2647.48   868.6 2652.49   892.3 2661.05
   912.2 2662.94  1008.7 2695.35  1043.9 2702.87  1113.4 2725.99  1138.2 2731.43
#Mann= 3 , 0 , 0
       0     .12       0   600.6     .04       0   615.8     .12       0
#XS Ineff= 2 , 0
          580.43 2645.65   631.3         2644.93
Permanent Ineff=
       F       F
Bank Sta=600.6,615.8
XS Rating Curve= 0 ,0
Exp/Cntr(USF)=0,0
Exp/Cntr=0.5,0.3

Type RM Length L Ch R = 1 ,28      ,,,
XS GIS Cut Line= 4
2124060.90301108453925.0288326072123431.87361147453756.037132078
  2123160.743296 453851.518239852122828.36094913454025.365917209
#Sta/Elev= 30
       0 2714.42   136.5 2678.45   207.8 2666.11     252 2662.89   272.6 2658.05
   336.5 2656.29   381.1 2646.75   411.8 2649.06   435.9 2644.12   459.2 2643.79
   479.6 2647.22   503.4 2643.14   538.8 2646.47   574.7 2643.35   631.4 2642.51
   651.3 2636.02     759 2632.34   802.5 2632.66   959.7 2631.47   997.3 2636.35
  1030.6 2636.03  1057.7 2642.65    1101  2645.2  1112.1 2644.24  1128.5 2637.56
  1142.6 2636.76  1168.8 2644.78  1200.4 2663.77  1249.4 2688.191313.887 2707.83
#Mann= 3 , 0 , 0
       0     .12       0     759     .04       0   802.5     .12       0
Bank Sta=759,802.5
XS Rating Curve= 0 ,0
Exp/Cntr(USF)=0,0
Exp/Cntr=0.3,0.1
LCMann Table=0

Chan Stop Cuts=-1
Use User Specified Reach Order=0
Composite Channel Slope=5